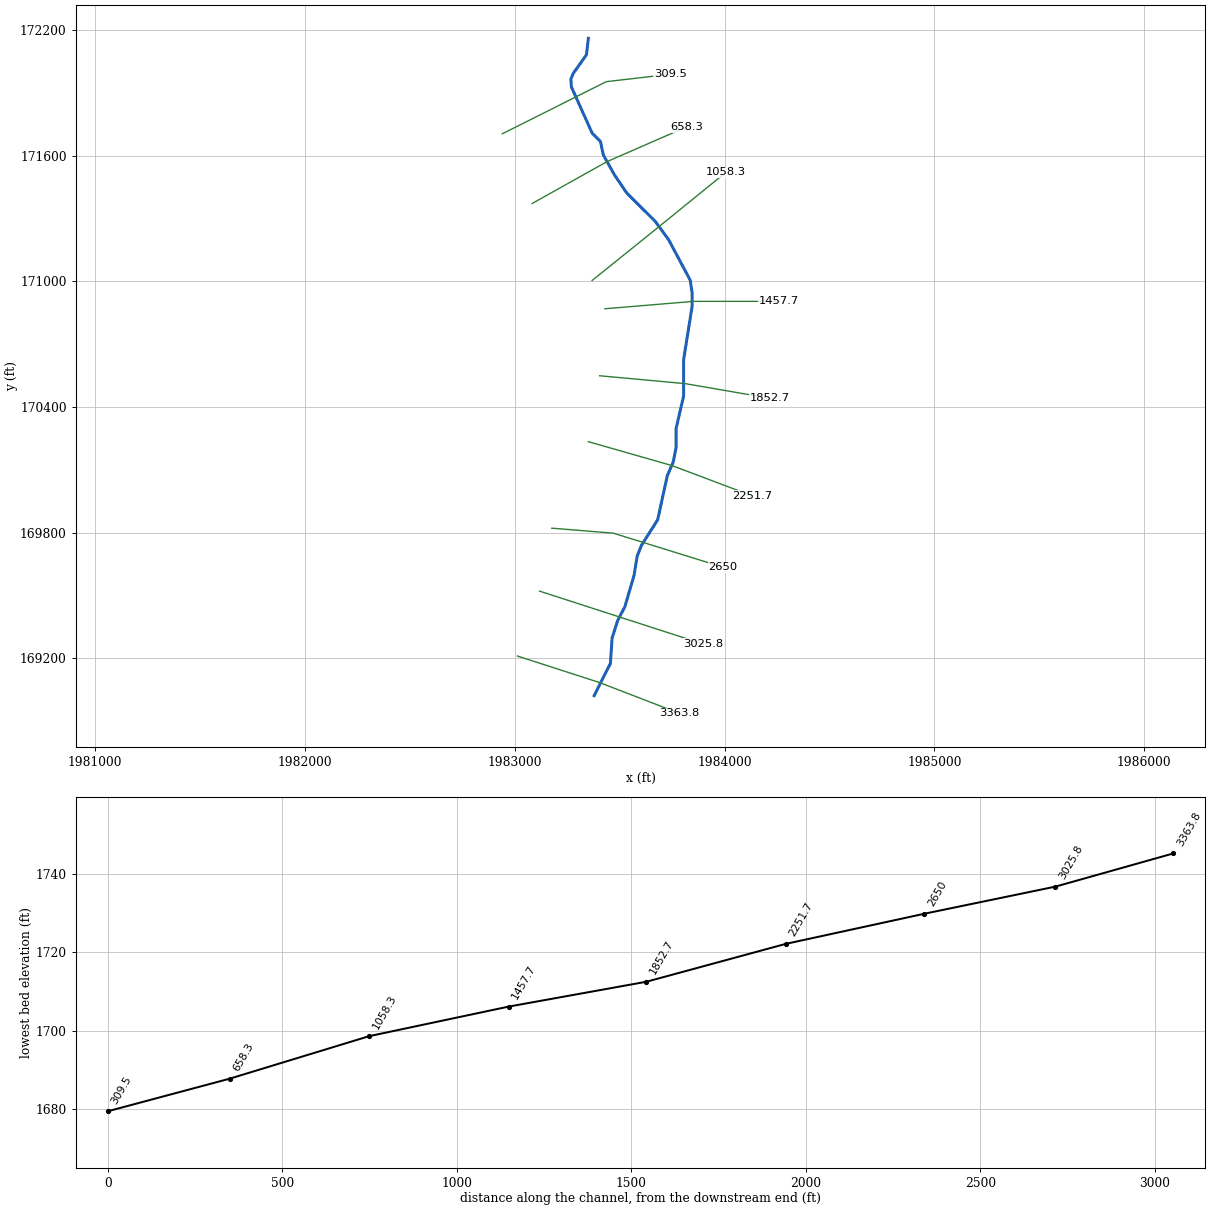
--- OvrlckCrk.prj (project) ---

Proj Title=OvrlckCrk
Current Plan=p01
Default Exp/Contr=0,0
English Units
Geom File=g01
Flow File=f01
Plan File=p01
BEGIN DESCRIPTION:
END DESCRIPTION:
DSS Export Rating Curves= 0
DSS Export Rating Curve Sorted= 0
DSS Export Volume Flow Curves= 0
DXF OffsetX= 0
DXF OffsetY= 0
DXF ScaleX= 0
DXF ScaleY= 0

--- OvrlckCrk.p01 (plan) ---

Plan Title=Floodplain
Program Version=4.00
Geom File=g01
Flow File=f01
K Sum by GR=0
Std Step Tol=0.01
Critical Tol=0.01
Num of Std Step Trials=20
Max Error Tol=0.3
Flow Tol Ratio=0.001
Split Flow NTrial=30
Split Flow Tol=0.02
Split Flow Ratio=0.02
Log Output Level=0
Friction Slope Method=1
Unsteady Friction Slope Method=2
Unsteady Bridges Friction Slope Method=1
Global Log Level=0
CheckData=False
Run HTab=0
Run UNet=0
Run PostProcess=0
UNET Theta=0
UNET Theta Warmup=0
UNET ZTol=0
UNET ZSATol=0
UNET MxIter=0
UNET MaxInSteps=0
UNET DtIC=0
UNET DtMin=0
UNET MaxCRTS=0
UNET WFStab=0
UNET SFStab=0
UNET WFX=0
UNET SFX=0
UNET DSS MLevel=0
UNET DZMax Abort=0
UNET Convert EG Bridges=0
UNET Use Existing IB Tables=0
UNET Froude Limit=0
UNET Froude Power=0
Write IC File=0
Echo Input=False
Echo Output=False
Write Detailed=0

--- OvrlckCrk.f01 (steady flow) ---

Flow Title=NFF Regression Equation
Program Version=4.00
Number of Profiles=1
Profile Names=P100yr
River Rch & RM=OvrlckCrk,Main      ,3363.8
500.4923
River Rch & RM=OvrlckCrk,Main      ,2650
515.0376
River Rch & RM=OvrlckCrk,Main      ,309.5
570.2210
Boundary for River Rch & Prof#=OvrlckCrk,Main      ,1
Up Type=0
Dn Type=3
Dn Slope=0.022934

--- OvrlckCrk.g01 (geometry) ---

Geom Title=USGS 3m DEM
Program Version=4.10

River Reach=OvrlckCrk       ,Main
Reach XY= 30
     1983378.548      169021.762     1983455.971      169175.598
     1983464.049      169296.767     1983490.975      169381.585
     1983524.871      169446.373     1983568.768      169596.467
     1983583.709       169688.78     1983604.571      169740.549
     1983681.312      169861.718     1983727.191      170072.423
     1983755.478        170137.5     1983768.962      170206.044
     1983768.857      170296.381      1983804.93      170452.768
      1983804.93      170626.038     1983845.619      170882.139
     1983845.619      170944.369     1983836.565      171006.017
     1983733.763      171199.239     1983669.651      171287.249
     1983533.518      171423.211     1983475.464       171509.21
     1983422.256      171604.158     1983408.949      171668.255
      1983369.32      171707.884     1983270.159      171929.194
     1983267.555      171966.954     1983279.274      171994.298
     1983341.774       172082.84     1983350.947      172161.369

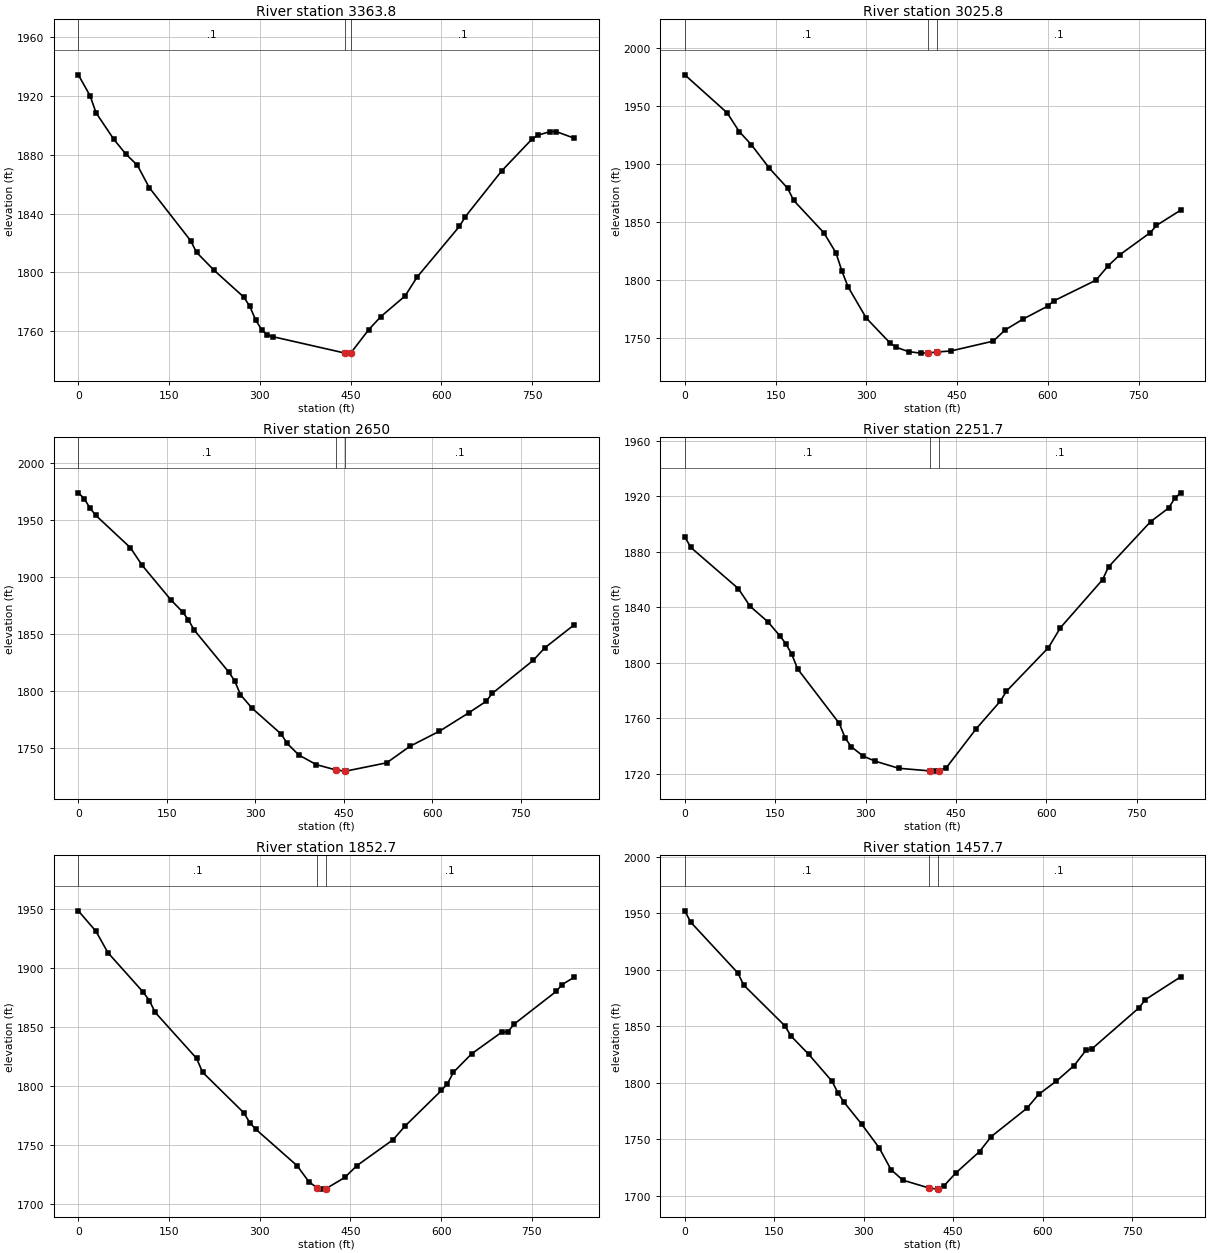
Type RM Length L Ch R = 1 ,3363.8  ,336.7,338,339.1
XS GIS Cut Line= 3
     1983012.711      169211.076     1983403.101      169084.842
     1983784.887      168937.143
#Sta/Elev= 30
       0 1934.42    19.5 1920.13    29.3 1908.58    58.6 1890.61    78.2 1880.68
    97.7 1872.87   117.2 1857.74   185.6 1821.64   195.4 1813.69   224.7 1801.38
   273.5 1783.27   283.3 1777.08   293.1  1767.7   302.8 1761.22   312.6 1757.46
   322.4 1756.26   440.2 1745.24   450.2 1745.16   480.2 1761.21   500.2 1770.05
   540.1 1784.02   560.1 1796.94     630 1831.38   639.9 1838.06   699.8 1869.08
   749.8 1890.68   759.8 1893.36   779.7 1895.83   789.7 1895.85   819.6 1891.34
#Mann= 3 , 0 , 0
       0      .1       0   440.2    .045       0   450.2      .1       0
Bank Sta=440.2,450.2
XS Rating Curve= 0 ,0
Exp/Cntr=0.3,0.1

Type RM Length L Ch R = 1 ,3025.8  ,376.7,375.5,375.9
XS GIS Cut Line= 3
     1983118.585      169520.982     1983508.145      169394.755
     1983897.705      169268.528
#Sta/Elev= 30
       0 1976.81    69.9 1944.05    89.9 1927.87   109.9 1916.52   139.8 1896.16
   169.8    1879   179.8 1868.48   229.7 1840.53   249.7 1823.22   259.7 1807.24
   269.7 1793.84   299.6 1767.06   339.6 1745.13   349.6 1741.66   369.6 1737.99
   389.5  1736.7     402 1736.85     417  1737.7   439.5 1738.56   509.4 1747.05
   529.4 1756.79   559.3 1766.22   599.3  1777.2   609.3  1781.7   679.2 1799.64
   699.2 1811.98   719.1 1821.77   769.1 1840.76     779 1846.83     819 1860.03
#Mann= 3 , 0 , 0
       0      .1       0     402    .045       0     417      .1       0
Bank Sta=402,417
XS Rating Curve= 0 ,0
Exp/Cntr=0.3,0.1

Type RM Length L Ch R = 1 ,2650    ,397.2,397.6,396.2
XS GIS Cut Line= 3
     1983176.415      169821.799     1983469.845      169797.899
     1983991.399      169635.661
#Sta/Elev= 30
       0 1973.61     9.8 1968.63    19.6  1960.4    29.4 1953.97    88.3 1925.52
     108 1910.23     157 1879.77   176.6 1869.36   186.4  1862.5   196.3 1853.51
   255.2 1816.48     265 1808.96   274.8 1796.82   294.4 1784.97   344.1 1762.17
     354 1754.07   373.8 1743.92   403.6 1735.47   436.6 1730.83   451.6 1729.81
   453.3 1729.79   522.8 1737.07   562.5 1751.67   612.2 1764.74   661.8 1780.84
   691.6 1791.02   701.6 1797.84   771.1 1826.79     791 1837.87   840.6 1857.95
#Mann= 3 , 0 , 0
       0      .1       0   436.6    .045       0   451.6      .1       0
Bank Sta=436.6,451.6
XS Rating Curve= 0 ,0
Exp/Cntr=0.3,0.1

Type RM Length L Ch R = 1 ,2251.7  ,394.8,399,403.9
XS GIS Cut Line= 3
     1983351.086      170234.894       1983749.1      170120.854
     1984131.585      169976.503
#Sta/Elev= 30
       0 1890.83     9.9 1883.08    88.7  1853.5   108.4 1840.71     138  1829.5
   157.7 1819.45   167.6 1813.86   177.4 1806.32   187.3 1795.61   256.3 1756.47
   266.2 1745.89     276 1739.76   295.7    1733   315.4 1729.33   354.9 1724.16
   406.5 1722.27     414  1722.1   421.5 1722.43     434 1724.57   483.8  1752.7
   523.7 1772.49   533.7 1779.55   603.5 1811.01   623.4 1825.31   693.2  1859.8
   703.2 1869.08     773 1901.64   802.9  1911.4   812.9 1918.32   822.8 1922.35
#Mann= 3 , 0 , 0
       0      .1       0   406.5    .045       0   421.5      .1       0
Bank Sta=406.5,421.5
XS Rating Curve= 0 ,0
Exp/Cntr=0.3,0.1

Type RM Length L Ch R = 1 ,1852.7  ,391,395,398.9
XS GIS Cut Line= 3
      1983404.62      170549.774     1983813.629      170511.952
     1984216.913      170442.155
#Sta/Elev= 30
       0  1948.2    29.3 1930.78    48.9 1912.76   107.6 1879.16   117.4 1872.21
   127.1 1862.19   195.6  1823.2   205.4 1811.54   273.8 1777.04   283.6 1768.73
   293.4 1763.21   361.9 1732.26   381.4 1718.61   394.5 1713.77     401 1712.46
   409.5 1712.82   440.7 1722.35   460.7 1732.38   520.6 1754.35   540.5 1765.96
   600.4 1796.01   610.4 1801.73   620.4 1811.44   650.3 1827.03   700.2  1845.4
   710.2  1845.5   720.2 1852.05   790.1 1879.87   800.1 1885.79     820 1891.88
#Mann= 3 , 0 , 0
       0      .1       0   394.5    .045       0   409.5      .1       0
Bank Sta=394.5,409.5
XS Rating Curve= 0 ,0
Exp/Cntr=0.3,0.1

Type RM Length L Ch R = 1 ,1457.7  ,385.9,399.4,414.1
XS GIS Cut Line= 3
     1983430.112      170869.817     1983853.492      170905.041
     1984260.285      170905.041
#Sta/Elev= 30
       0 1952.02     9.9 1942.03    88.9 1897.16    98.8 1886.43     168 1850.33
   177.8 1841.57   207.5  1825.4     247 1801.42   256.9  1791.1   266.8  1783.1
   296.4 1763.67     326 1742.61   345.8 1723.41   365.6 1714.07   409.4 1707.14
   424.4 1706.13   424.8 1706.12   434.8 1709.09   454.6 1720.41   494.3  1739.3
   514.1 1752.61   573.7 1777.54   593.5 1789.86   623.3 1801.62     653 1815.29
   672.9  1828.9   682.8 1830.05   762.2 1866.53   772.1 1873.44   831.6 1893.66
#Mann= 3 , 0 , 0
       0      .1       0   409.4    .045       0   424.4      .1       0
Bank Sta=409.4,424.4
XS Rating Curve= 0 ,0
Exp/Cntr=0.3,0.1

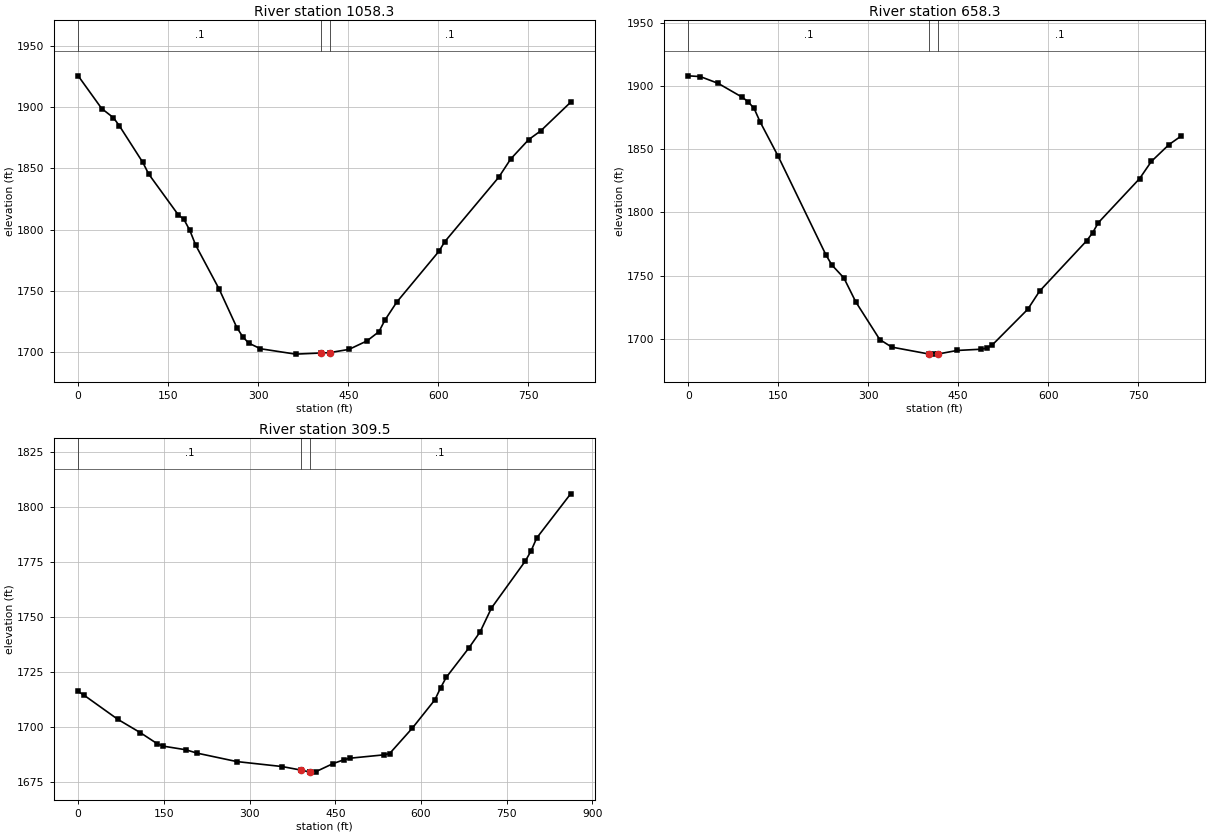
Type RM Length L Ch R = 1 ,1058.3  ,403.7,399.9,393.9
XS GIS Cut Line= 3
     1983369.193      171005.021     1983689.206      171263.199
     1984006.704      171521.353
#Sta/Elev= 30
       0 1925.41    39.2 1898.72    58.7 1891.29    68.5 1884.79   107.7 1854.84
   117.5 1845.35   166.4 1812.36   176.2 1808.37     186 1799.46   195.8 1787.38
     235 1751.45   264.3 1720.25   274.1  1712.8   283.9 1707.65   303.5 1702.99
   362.2 1698.59   403.7 1699.49   418.7 1699.78   451.1 1702.44     481 1709.34
     501 1716.86     511 1726.31   530.9 1741.11   600.8 1782.29   610.8 1790.29
   700.6 1842.76   720.6 1857.68   750.5 1873.45   770.5 1880.54   820.4  1903.9
#Mann= 3 , 0 , 0
       0      .1       0   403.7    .045       0   418.7      .1       0
Bank Sta=403.7,418.7
XS Rating Curve= 0 ,0
Exp/Cntr=0.3,0.1

Type RM Length L Ch R = 1 ,658.3   ,349.5,348.8,350.3
XS GIS Cut Line= 3
     1983083.169      171372.554      1983439.99      171572.513
     1983817.589      171737.744
#Sta/Elev= 30
       0 1908.27      20 1907.67    49.9 1902.28    89.8 1891.34    99.8 1887.73
   109.7 1882.45   119.7 1871.82   149.6 1844.77   229.5 1766.38   239.4 1758.37
   259.4 1748.15   279.3 1729.12   319.2 1699.33   339.2 1693.32   401.5 1687.81
     409 1687.75   416.5 1687.85   448.3 1690.66   487.5 1691.62   497.4 1692.53
   507.2 1695.18     566 1723.28   585.7 1737.64   664.2 1777.54     674 1783.78
   683.8 1791.94   752.5 1826.81   772.1 1840.43   801.6 1853.81   821.2 1860.36
#Mann= 3 , 0 , 0
       0      .1       0   401.5    .045       0   416.5      .1       0
Bank Sta=401.5,416.5
XS Rating Curve= 0 ,0
Exp/Cntr=0.3,0.1

Type RM Length L Ch R = 1 ,309.5   ,319.3,309.4,299.6
XS GIS Cut Line= 3
     1982940.303      171705.203     1983436.337      171954.411
     1983741.196        171989.7
#Sta/Elev= 30
       0 1716.13     9.9  1714.5    69.4 1703.46     109 1697.37   138.8  1692.3
   148.7 1691.28   188.3 1689.63   208.2 1688.09   277.6 1684.26   356.9    1682
   390.1 1680.38   405.1 1679.52   406.4 1679.46   416.3  1679.7   446.1 1683.34
   465.9 1685.15   475.8 1685.79   535.3 1687.32   545.2 1687.92   584.8 1699.44
   624.4 1712.36   634.3 1717.76   644.2 1722.53   683.8 1735.89   703.6 1743.25
   723.4 1754.08   782.8 1775.48   792.7 1780.04   802.6 1785.91     862 1805.98
#Mann= 3 , 0 , 0
       0      .1       0   390.1    .045       0   405.1      .1       0
Bank Sta=390.1,405.1
XS Rating Curve= 0 ,0
Exp/Cntr=0.3,0.1

Chan Stop Cuts=-1
Use User Specified Reach Order=0
Composite Channel Slope=5